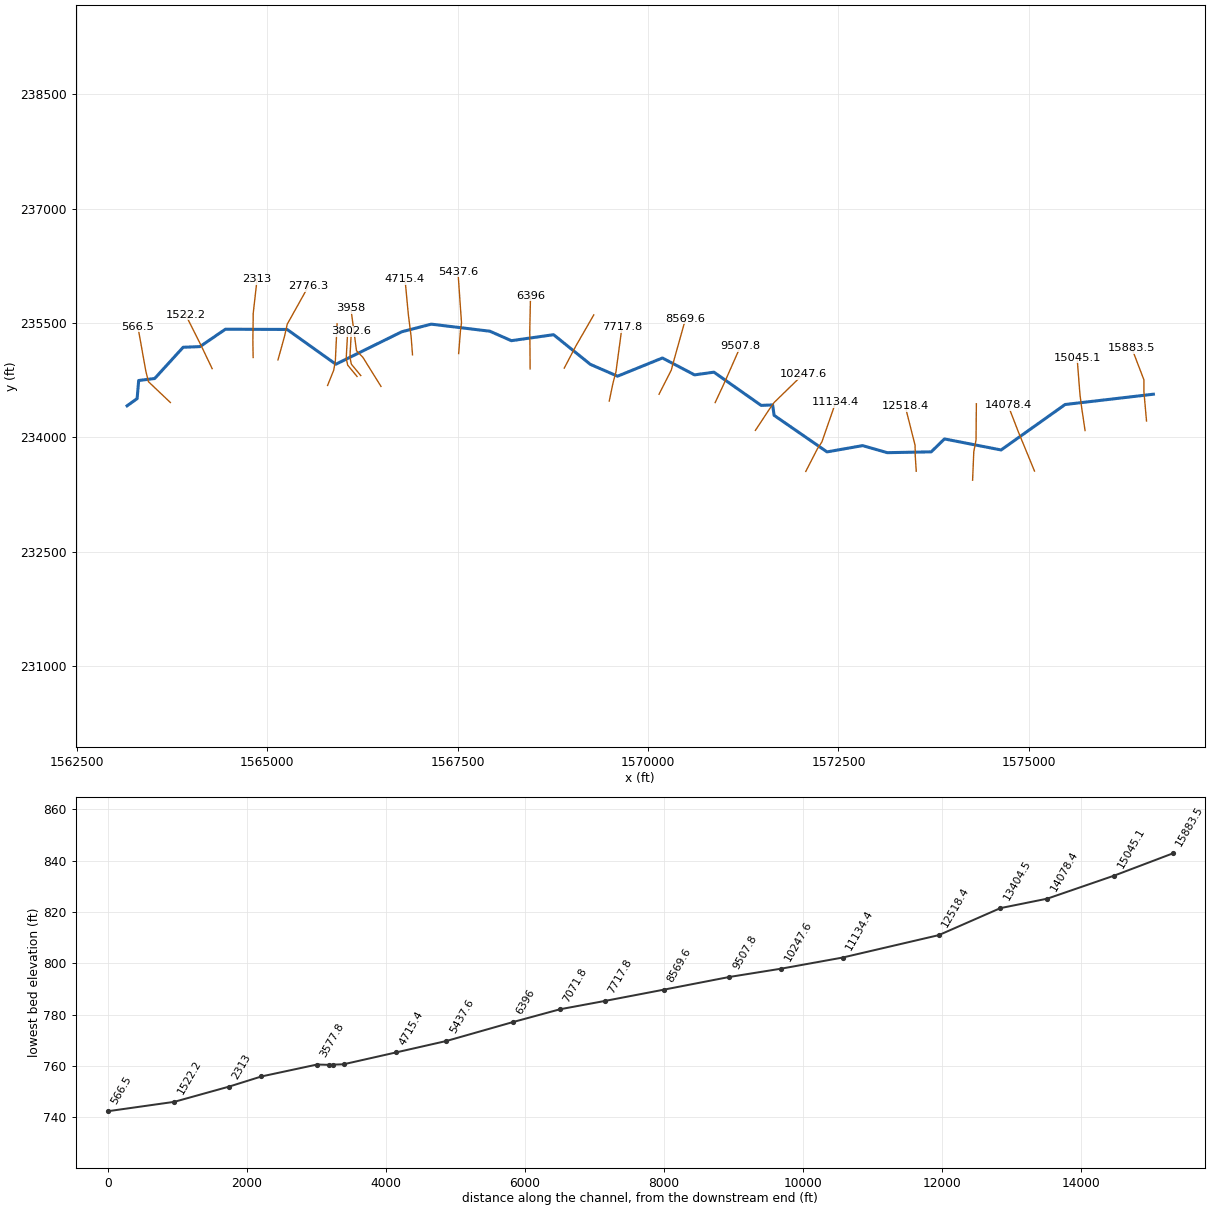
--- OTTRSLDCR.prj (project) ---

Proj Title=OTTRSLDCR
Current Plan=p01
Default Exp/Contr=0,0
English Units
Geom File=g01
Flow File=f01
Plan File=p01
BEGIN DESCRIPTION:
END DESCRIPTION:
DSS Export Rating Curves= 0
DSS Export Rating Curve Sorted= 0
DSS Export Volume Flow Curves= 0
DXF OffsetX= 0
DXF OffsetY= 0
DXF ScaleX= 0
DXF ScaleY= 0

--- OTTRSLDCR.p01 (plan) ---

Plan Title=Floodplain
Program Version=4.00
Geom File=g01
Flow File=f01
K Sum by GR=0
Std Step Tol=0.01
Critical Tol=0.01
Num of Std Step Trials=20
Max Error Tol=0.3
Flow Tol Ratio=0.001
Split Flow NTrial=30
Split Flow Tol=0.02
Split Flow Ratio=0.02
Log Output Level=0
Friction Slope Method=1
Unsteady Friction Slope Method=2
Unsteady Bridges Friction Slope Method=1
Global Log Level=0
CheckData=False
Run HTab=0
Run UNet=0
Run PostProcess=0
UNET Theta=0
UNET Theta Warmup=0
UNET ZTol=0
UNET ZSATol=0
UNET MxIter=0
UNET MaxInSteps=0
UNET DtIC=0
UNET DtMin=0
UNET MaxCRTS=0
UNET WFStab=0
UNET SFStab=0
UNET WFX=0
UNET SFX=0
UNET DSS MLevel=0
UNET DZMax Abort=0
UNET Convert EG Bridges=0
UNET Use Existing IB Tables=0
UNET Froude Limit=0
UNET Froude Power=0
Write IC File=0
Echo Input=False
Echo Output=False
Write Detailed=0

--- OTTRSLDCR.f01 (steady flow) ---

Flow Title=NFF Regression Equation
Program Version=4.10
Number of Profiles= 1
Profile Names=P100yr
River Rch & RM=OTTRSLDCR,Main            ,15883.5
967.8328
River Rch & RM=OTTRSLDCR,Main            ,11134.4
1065.201
River Rch & RM=OTTRSLDCR,Main            ,8569.6
1118.431
River Rch & RM=OTTRSLDCR,Main            ,7717.8
1218.137
River Rch & RM=OTTRSLDCR,Main            ,6396
1269.319
River Rch & RM=OTTRSLDCR,Main            ,3958
1356.375
River Rch & RM=OTTRSLDCR,Main            ,3577.8
1461.594
River Rch & RM=OTTRSLDCR,Main            ,566.5
1535.764
Boundary for River Rch & Prof#=OTTRSLDCR,Main            , 1
Up Type= 0
Dn Type= 3
Dn Slope=0.00372
DSS Import GetInterval= 0
DSS Import GetPeak= 0
DSS Import FillOption= 0

--- OTTRSLDCR.g01 (geometry) ---

Geom Title=USGS 10m DEM
Program Version=4.10

River Reach=OTTRSLDCR       ,Main
Reach XY= 30
     1576635.385      234564.304     1575476.078      234429.143
     1574635.391      233832.777     1573891.804      233977.625
     1573718.252      233808.171     1573140.671      233797.219
      1572816.71      233889.815     1572349.502      233807.477
     1571654.901      234287.037     1571635.434      234423.454
     1571484.632      234417.559     1570864.719      234853.583
     1570610.614      234817.893     1570188.131      235039.421
     1569598.966      234800.639     1569241.633      234956.212
     1568758.853      235345.317     1568204.535      235266.514
     1567922.474      235390.762     1567153.387      235483.405
     1566766.135      235383.743      1565900.11       234957.65
     1565260.006        235413.9     1564450.163      235416.986
     1564116.256        235188.9     1563895.013      235180.149
     1563521.117       234770.15     1563311.048      234744.109
     1563290.467      234506.381     1563159.085       234412.58

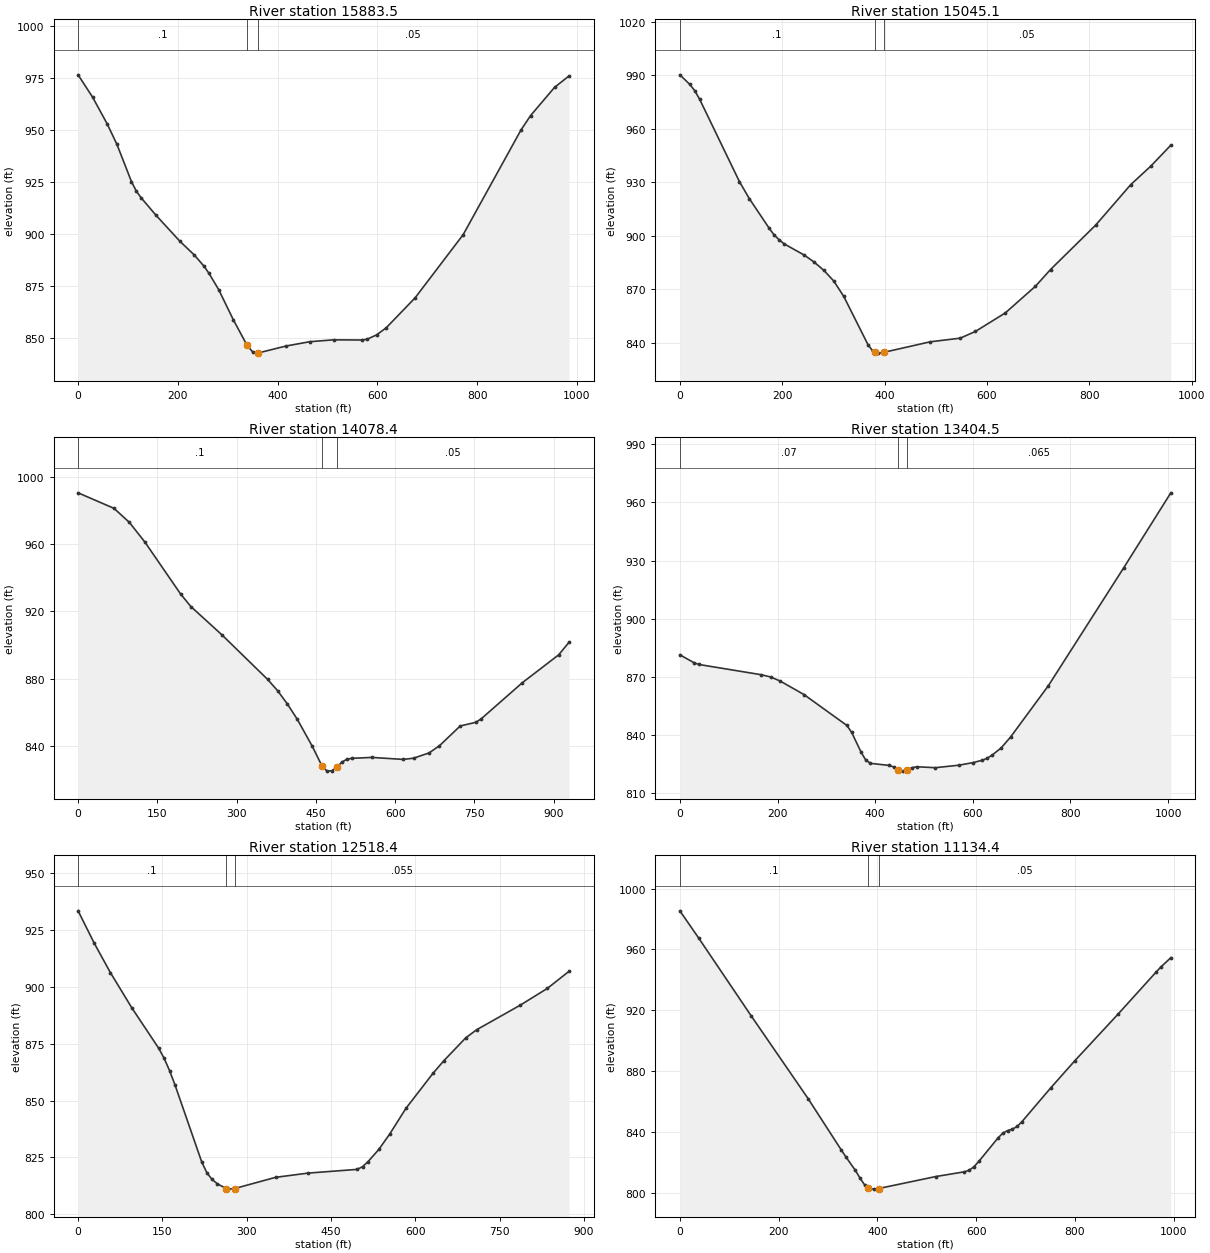
Type RM Length L Ch R = 1 ,15883.5 ,837.8,838.5,839.2
XS GIS Cut Line= 4
     1576545.113      234212.551     1576511.259      234590.155
     1576511.259      234751.613     1576352.404      235165.676
#Sta/Elev= 30
       0  976.45    29.2  965.68    58.3   952.9    77.8  943.11   106.9  925.24
   116.6  920.67   126.4  917.41   155.5  909.22   204.1  896.54   233.3  889.88
   252.8  884.46   262.5  881.11   281.9   873.3   311.1   858.9   338.8  846.55
     350  843.42   359.7  842.85   417.1  846.28   464.6  848.34   512.1  849.23
   569.5  849.14   579.1   849.5   598.4  851.61   617.7  855.02   675.6  869.41
     772  899.78   887.7  949.94   906.9  956.86   955.1  970.44   984.1  975.93
#Mann= 3 , 0 , 0
       0      .1       0   338.8    .045       0   359.7     .05       0
Bank Sta=338.8,359.7
XS Rating Curve= 0 ,0
Exp/Cntr=0.3,0.1

Type RM Length L Ch R = 1 ,15045.1 ,960.2,966.6,972.1
XS GIS Cut Line= 4
     1575737.821      234087.551     1575688.342      234423.488
     1575670.113      234571.926     1575633.654      235040.676
#Sta/Elev= 30
       0  990.14    19.4  984.78    29.1  981.27    38.8  976.36   116.4   930.3
   135.8  920.74   174.6  904.15   184.3  900.41     194   897.7   203.7  895.45
   242.5  889.25     262  885.32   281.4  880.59   300.8  874.59   320.2  866.02
   367.6  838.96     377  835.36   380.3  834.96   386.3  834.23  398.42 834.675
   489.1  840.57   547.9  842.62   577.3  846.35     636  856.78   694.8   871.7
   724.2  881.06   812.4  905.93   880.9   928.6   920.1  938.97   959.3  950.72
#Mann= 3 , 0 , 0
       0      .1       0   380.3    .045       0  398.42     .05       0
Bank Sta=380.3,398.42
XS Rating Curve= 0 ,0
Exp/Cntr=0.3,0.1

Type RM Length L Ch R = 1 ,14078.4 ,687.1,674,660.4
XS GIS Cut Line= 4
     1575073.759      233556.301     1574940.946      233879.218
     1574865.425      234061.509     1574727.404       234418.28
#Sta/Elev= 30
       0   990.4    67.9   981.2      97  972.88   126.1   961.3     194  930.35
   213.4   922.9   271.6  906.27   358.6  879.67   377.4     873   396.1  865.02
   414.9  855.91   443.1  839.98     462  827.95   471.3   825.2   480.7  825.44
   490.1  827.78   499.5  830.63   508.9  832.28   518.3  832.82   556.3  833.34
   615.1  832.15   634.8  832.88   664.2  836.02   683.8  840.28     723  851.99
   752.5  854.17   762.3  856.11   840.7  877.71   909.4  894.24     929  901.72
#Mann= 3 , 0 , 0
       0      .1       0     462    .045       0   490.1     .05       0
Bank Sta=462,490.1
XS Rating Curve= 0 ,0
Exp/Cntr=0.3,0.1

Type RM Length L Ch R = 1 ,13404.5 ,881,886.1,890.6
XS GIS Cut Line= 4
     1574261.259      233436.509     1574276.739      233807.603
     1574306.398      233966.023     1574310.738      234439.113
#Sta/Elev= 30
       0  881.46    29.3  877.35    39.1  876.48   166.2  871.22   185.7  870.05
   205.3  867.97   254.1     861   342.1  845.06   351.9  841.48   371.4  831.17
   380.9  827.19   390.4  825.52   428.3  824.47   437.8  823.69   447.3  822.26
   456.7  821.51   466.2  822.27   475.7  823.28   485.2  823.76   523.1  823.28
   571.2  824.56   600.2  825.88   619.5  827.12   629.1  828.14   638.8   829.6
   658.1  833.46   677.4  839.08   754.7  865.49   909.2  926.32  1005.7  964.96
#Mann= 3 , 0 , 0
       0     .07       0   447.3    .045       0   466.2    .065       0
Bank Sta=447.3,466.2
XS Rating Curve= 0 ,0
Exp/Cntr=0.3,0.1

Type RM Length L Ch R = 1 ,12518.4 ,1386.7,1383.9,1368.4
XS GIS Cut Line= 4
     1573521.392      233553.526     1573508.371      233754.047
     1573505.767      233894.672     1573375.558      234410.297
#Sta/Elev= 30
       0  933.52    28.7  919.28    57.4  906.35    95.7  890.76   143.5  872.98
   153.1  868.57   162.7  863.18   172.2     857   219.7  823.12   229.1  818.16
   238.4  815.24   247.8  813.32   263.7  811.21   266.6  810.98   278.7  811.25
   351.3  816.17   409.3  818.04   496.3  819.67     506  820.85   515.6  823.02
     535  828.45   554.3  835.21   583.3  846.57   631.7  862.08     651   867.6
   689.7  877.61     709  881.15   786.4  891.95   834.7  899.34   873.4   906.9
#Mann= 3 , 0 , 0
       0      .1       0   263.7    .045       0   278.7    .055       0
Bank Sta=263.7,278.7
XS Rating Curve= 0 ,0
Exp/Cntr=0.3,0.1

Type RM Length L Ch R = 1 ,11134.4 ,887.9,886.9,887.8
XS GIS Cut Line= 4
     1572070.871      233550.922     1572224.517      233850.401
     1572281.798      233936.794       1572464.1      234459.776
#Sta/Elev= 30
       0  985.35    38.5  967.23   144.2  916.34   259.7  861.75     327   827.9
   336.6  823.23   355.4  814.55   364.9  809.44   374.3  804.94   381.5  803.13
   383.7  802.58   393.1  802.23   402.6  802.64     518   810.5   576.3  813.64
     586  814.68   595.7  817.03   605.4  820.52   644.3  835.96     654  839.06
   663.7  840.75   673.4  841.71   683.2  843.53   692.9  846.72   751.2  868.95
   799.8  886.75   887.2  917.37     965  945.31   974.7  948.65   994.1   954.5
#Mann= 3 , 0 , 0
       0      .1       0   381.5    .045       0   402.6     .05       0
Bank Sta=381.5,402.6
XS Rating Curve= 0 ,0
Exp/Cntr=0.3,0.1

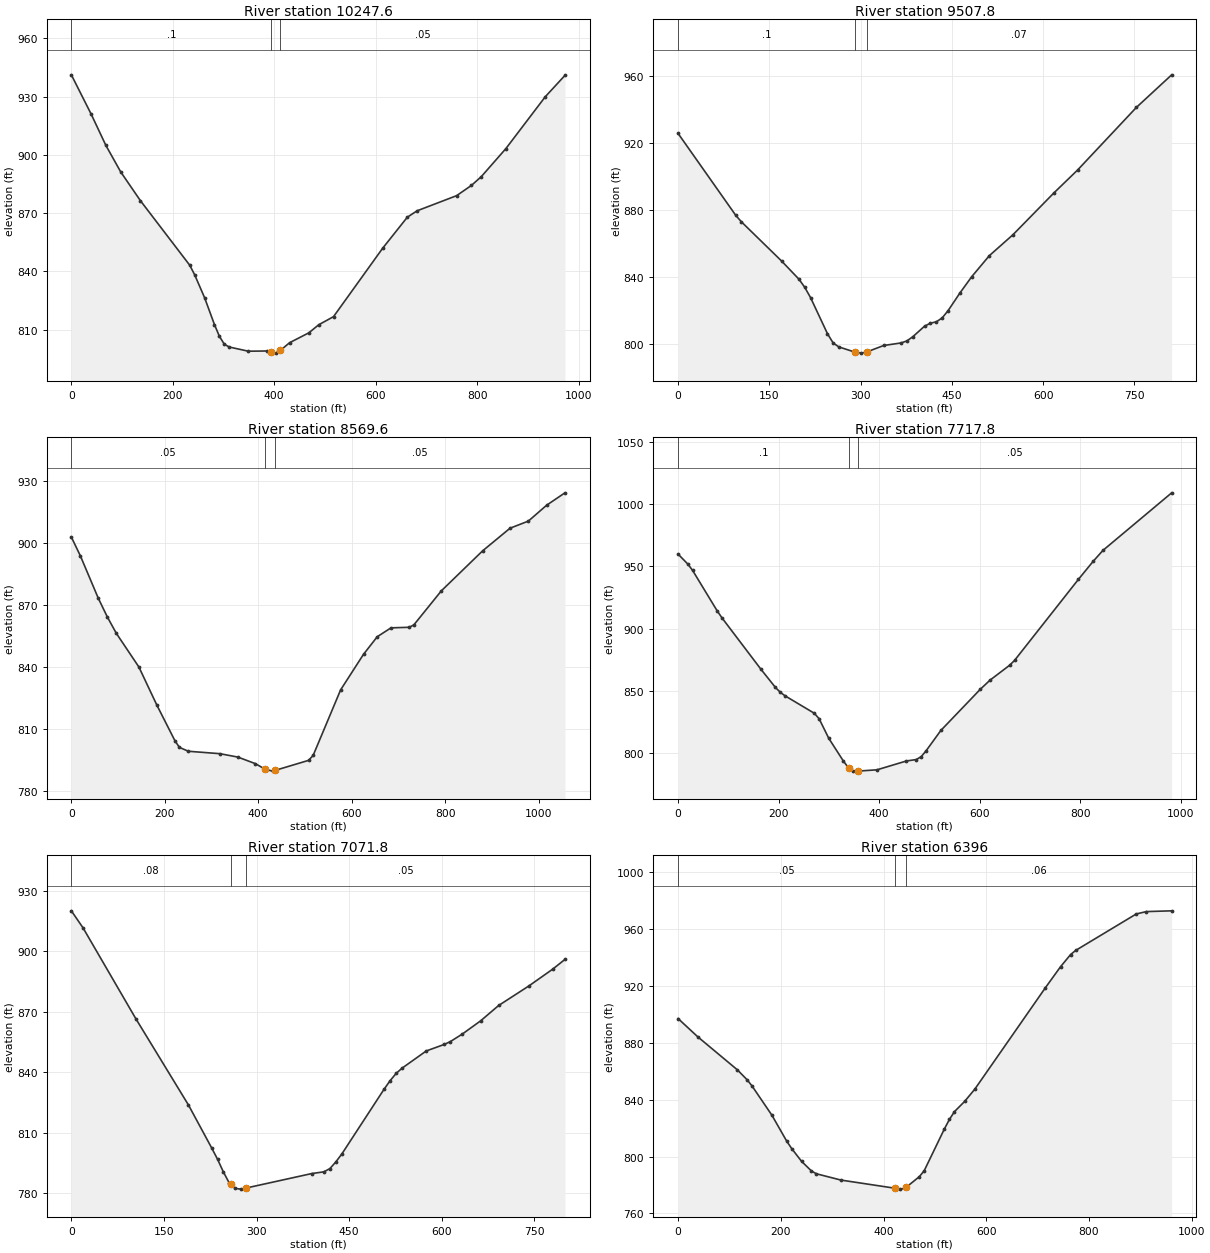
Type RM Length L Ch R = 1 ,10247.6 ,734.9,739.8,744.6
XS GIS Cut Line= 4
     1571409.413      234089.984     1571591.704      234366.026
     1571654.204      234454.568     1572037.017      234826.964
#Sta/Elev= 30
       0   941.2    38.9  921.05    68.1  904.85    97.3  891.22   136.2  876.39
   233.5  843.12   243.2  838.18   262.7  826.43   282.2  812.55   291.9  806.54
   301.6  802.47   311.3  801.03   348.9  798.87     385  798.98     394  798.29
     403  797.88   412.1  799.27   430.2  803.23   468.3  808.34   487.7  812.48
   516.9  816.66     614  851.97   662.5   867.9   681.9   871.2   759.6  878.97
   788.8  884.25   808.2  888.75   856.7   903.2   934.4  929.91   973.2  940.91
#Mann= 3 , 0 , 0
       0      .1       0     394    .045       0   412.1     .05       0
Bank Sta=394,412.1
XS Rating Curve= 0 ,0
Exp/Cntr=0.3,0.1

Type RM Length L Ch R = 1 ,9507.8  ,928.9,938.2,885.6
XS GIS Cut Line= 4
     1570880.767      234454.568     1570977.121      234660.297
       1571026.6      234769.672       1571214.1      235194.151
#Sta/Elev= 30
       0  925.54    94.7   876.8   104.1  872.88   170.4  849.44   198.8  838.66
   208.2  833.87   217.7  827.78   245.6  806.21   254.9  800.72   264.1   798.4
     290  795.34     301  794.67   310.3  795.39     338  799.22   366.6  800.74
   376.2  801.96   385.9  804.46   405.2  810.74   414.9  812.51   424.6  813.34
   434.2  815.68   443.9  820.02   463.2  830.46   482.6  840.17   511.6  852.72
   550.2  865.11   617.9  890.15   656.6  903.71   753.3  941.02   811.3  960.43
#Mann= 3 , 0 , 0
       0      .1       0     290    .045       0   310.3     .07       0
Bank Sta=290,310.3
XS Rating Curve= 0 ,0
Exp/Cntr=0.3,0.1

Type RM Length L Ch R = 1 ,8569.6  ,850.4,851.8,850.4
XS GIS Cut Line= 4
     1570143.788      234563.943     1570305.246      234881.651
     1570331.288      234980.609     1570492.746       235556.13
#Sta/Elev= 30
       0  903.07    19.3  893.98    57.8  873.38    77.1  864.35    96.3  856.45
   144.5  840.18     183  821.71   221.5  804.54   231.2  801.25   250.4  799.36
   317.8  798.19   356.4  796.54   393.6  793.38   414.9  790.65   430.8  789.74
  435.38790.0503   507.7  794.95   517.5  797.35   576.3  829.09   625.3  846.31
   654.7  854.82   684.1  859.11   723.3  859.39   733.1  860.57   791.9  877.04
   880.1  896.38   938.9  907.36   978.1   910.8  1017.2  918.49  1056.4  924.49
#Mann= 3 , 0 , 0
       0     .05       0   414.9    .045       0  435.38     .05       0
Bank Sta=414.9,435.38
XS Rating Curve= 0 ,0
Exp/Cntr=0.3,0.1

Type RM Length L Ch R = 1 ,7717.8  ,651.1,646.1,640.9
XS GIS Cut Line= 4
     1569490.142       234474.88     1569539.621      234711.859
     1569578.683      234860.297     1569656.808      235441.026
#Sta/Elev= 30
       0  959.98    19.4  951.94      29  946.77    77.5  914.47    87.2   908.7
   164.6  867.39   193.7  852.62   203.4  848.72     213  845.85   270.9  831.89
   280.5  827.46   299.6  811.78   328.4  793.62   339.6  787.58   347.6  785.39
   357.2  785.32   395.6  786.38   454.2   793.5   473.7  794.64   483.5  796.99
   493.2  801.69   522.5  818.04   600.7  851.07   620.2   858.5   659.3  870.52
     669  874.39     796   939.6   825.3   954.1   844.8  962.93   981.5 1009.27
#Mann= 3 , 0 , 0
       0      .1       0   339.6    .045       0   357.2     .05       0
Bank Sta=339.6,357.2
XS Rating Curve= 0 ,0
Exp/Cntr=0.3,0.1

Type RM Length L Ch R = 1 ,7071.8  ,664,675.7,686.6
XS GIS Cut Line= 4
     1568898.919      234906.298     1569004.741      235107.688
      1569048.24       235190.47     1569287.017      235605.089
#Sta/Elev= 30
       0  920.07      19  911.59   104.3  866.65   189.6  823.84   227.5  802.37
   236.8  796.89   246.2  790.62   255.6   785.2   257.9  784.52   264.9  782.46
   274.3  782.07   283.6  782.65   389.4  789.79   408.9  790.64   418.7  792.23
   428.4  795.57   438.2  799.54   506.5   831.6   516.3  835.84   526.1  839.47
   535.8  842.08   574.9  850.59   604.2  853.84     614  855.25   633.5  859.02
   662.8  865.49   692.1  873.13   740.9  882.79   779.9   891.2   799.5  895.98
#Mann= 3 , 0 , 0
       0     .08       0   257.9    .045       0   283.6     .05       0
Bank Sta=257.9,283.6
XS Rating Curve= 0 ,0
Exp/Cntr=0.3,0.1

Type RM Length L Ch R = 1 ,6396    ,960.9,958.4,953.5
XS GIS Cut Line= 4
     1568451.079      234896.755     1568448.475      235271.755
     1568445.871      235375.922     1568456.288      235857.693
#Sta/Elev= 30
       0  896.91    38.5  884.04   115.4  860.91   134.6  853.85   144.2  849.46
   182.7  829.01   211.5  810.82   221.2   805.6   240.4  796.64   259.6  789.88
   269.2  787.88   317.3  783.44   422.4  777.72   431.8  777.09   441.3  777.58
  444.73  778.56   469.7  785.82   479.2  789.98   518.6  819.41   528.4  826.08
   538.2  831.53   557.9  838.68   577.6  847.22   715.2  918.54   744.7  933.31
   764.4   941.9   774.2  944.77   892.2  970.39   911.9  972.04   961.1  972.58
#Mann= 3 , 0 , 0
       0     .05       0   422.4    .045       0  444.73     .06       0
Bank Sta=422.4,444.73
XS Rating Curve= 0 ,0
Exp/Cntr=0.3,0.1

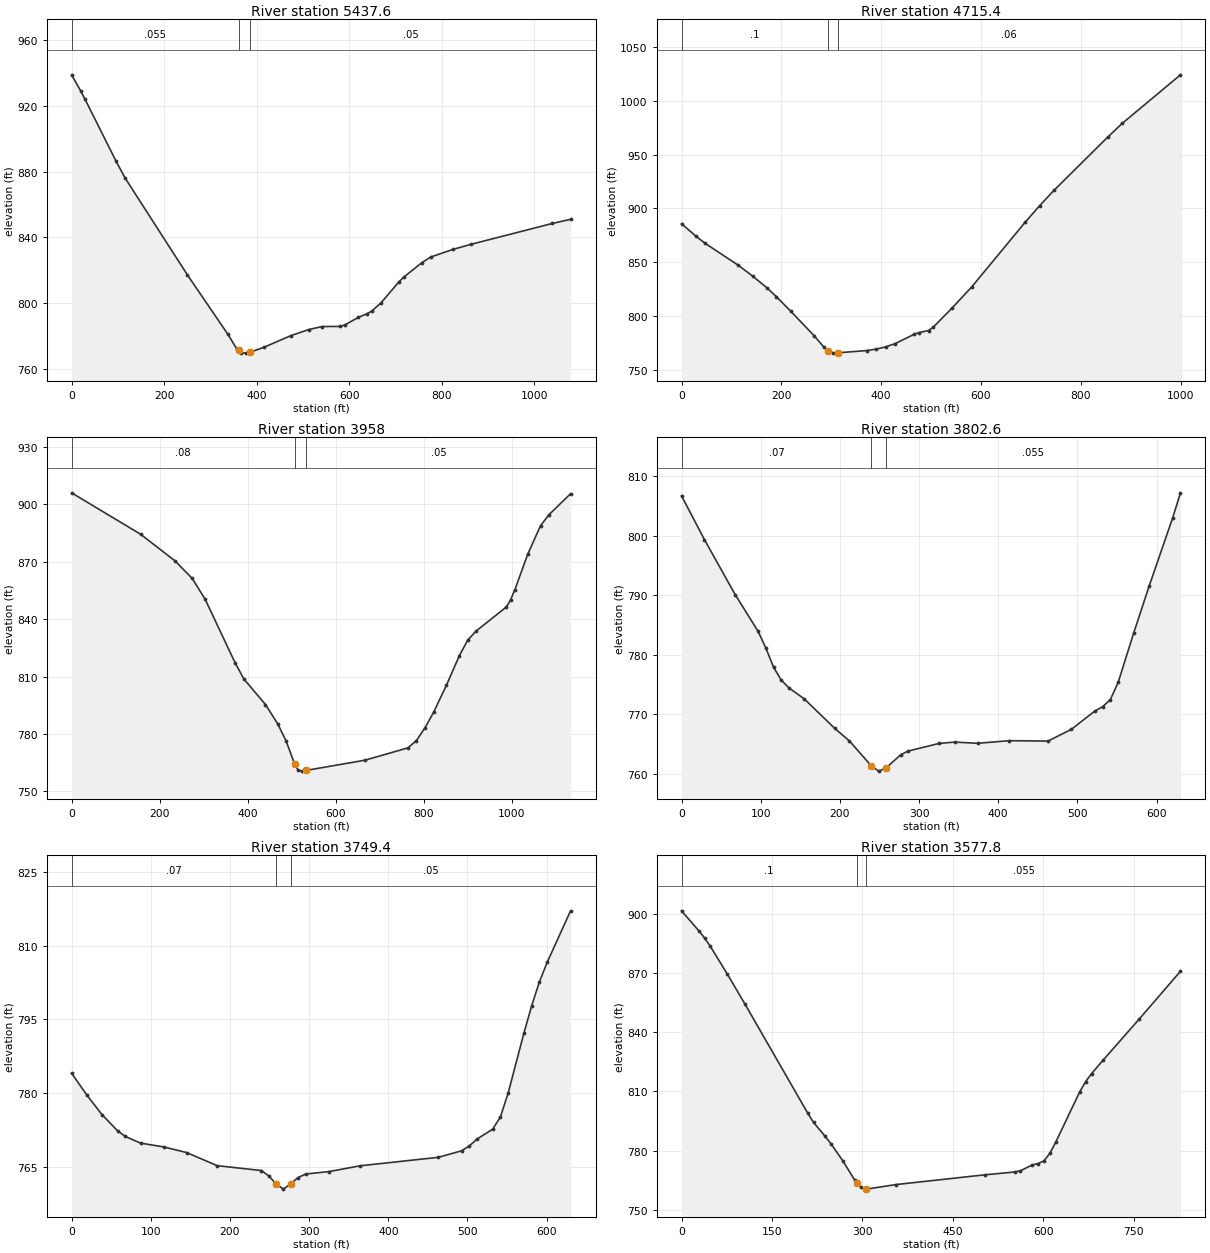
Type RM Length L Ch R = 1 ,5437.6  ,716.3,722.2,726.1
XS GIS Cut Line= 4
     1567512.711      235098.144     1567536.149      235395.887
     1567550.038       235501.79     1567503.163      236173.665
#Sta/Elev= 30
       0  938.72    19.3  929.12    28.9  923.96    96.3  886.17   115.6  876.08
   250.5  817.16   337.5  781.32   356.9  772.42   360.9   771.4   366.6  769.94
   376.3   769.7     386  770.24   415.2  773.17   473.8  780.28   512.8  784.03
   542.1  785.85   581.2  785.91   590.9  786.85   620.2  791.42   639.7  793.69
   649.5  795.36     669  800.21   708.1  813.08   717.8  815.74   756.9  824.54
   776.4  828.05   825.2  832.75   864.2  835.82  1039.9  848.47    1079  850.97
#Mann= 3 , 0 , 0
       0    .055       0   360.9    .045       0     386     .05       0
Bank Sta=360.9,386
XS Rating Curve= 0 ,0
Exp/Cntr=0.3,0.1

Type RM Length L Ch R = 1 ,4715.4  ,741.2,757.5,769.8
XS GIS Cut Line= 4
     1566906.808      235081.651     1566888.579       235318.63
     1566851.777      235611.761      1566807.85      236076.443
#Sta/Elev= 30
       0  885.62    28.5   874.2    47.5  867.34   114.1  846.89   142.6  836.88
   171.1  826.05   190.1  817.75   218.7  804.33   266.3  781.17   285.3  770.79
   293.5  767.23   294.9  766.62   304.4  765.25   313.9  765.56   371.1  767.64
   390.2  768.97   409.2  771.07   428.3  774.12   466.4  782.82   475.9  784.32
     495  786.28   504.5  789.43   542.8  807.49   581.7  826.91   688.7  887.02
   717.9  902.52     747  916.94     854  966.12   883.2  978.98   999.9 1024.13
#Mann= 3 , 0 , 0
       0      .1       0   293.5    .045       0   313.9     .06       0
Bank Sta=293.5,313.9
XS Rating Curve= 0 ,0
Exp/Cntr=0.3,0.1

Type RM Length L Ch R = 1 ,3958    ,167.7,155.3,142.7
XS GIS Cut Line= 4
     1566492.746       234666.72     1566254.899      235048.665
     1566171.565      235133.734     1566096.913      235692.762
#Sta/Elev= 30
       0  905.96   156.5  884.35   234.8  870.43   273.9  861.23   303.2  850.38
   371.7  816.97   391.3  808.71   440.2   795.4   468.3  785.18   486.6  776.59
   506.4  764.37   514.1  761.16   523.2  760.61   532.4  760.98   666.3  766.33
   763.5  772.74     783  776.56   802.4  783.22   821.9  791.29     851  805.39
   880.2  820.76   899.6  829.11   919.1  833.89   987.2  846.33   996.9  850.12
  1006.6   855.4  1035.8  873.94    1065  888.88  1084.4  894.62    1133  905.48
#Mann= 3 , 0 , 0
       0     .08       0   506.4    .045       0   532.4     .05       0
Bank Sta=506.4,532.4
XS Rating Curve= 0 ,0
Exp/Cntr=0.3,0.1

Type RM Length L Ch R = 1 ,3802.6  ,53.4,53.2,51.3
XS GIS Cut Line= 4
     1566227.121      234809.082     1566103.857      234958.387
      1566084.76      235048.665     1566103.857      235392.415
#Sta/Elev= 30
       0  806.66      29   799.3    67.8  790.08    96.8  783.91   106.5  781.13
   116.2  777.92   125.8  775.77   135.5  774.45   154.9  772.61   193.6  767.63
   212.1  765.53   239.8  761.34     249  760.47   258.2     761   276.7  763.19
   285.9  763.83   325.2  765.11   344.9  765.34   374.4  765.14   413.8  765.58
     463  765.51   492.5  767.49     522  770.55   531.8  771.27   541.6  772.46
   551.5  775.36   571.2  783.67   590.8  791.58   620.3  802.94   630.2  807.16
#Mann= 3 , 0 , 0
       0     .07       0   239.8    .045       0   258.2    .055       0
Bank Sta=239.8,258.2
XS Rating Curve= 0 ,0
Exp/Cntr=0.3,0.1

Type RM Length L Ch R = 1 ,3749.4  ,180.3,171.6,163.8
XS GIS Cut Line= 4
      1566178.51      234796.929     1566055.246      234946.234
     1566036.149      235036.512     1566055.246      235380.262
#Sta/Elev= 30
       0  784.02    19.4  779.53    38.7  775.52    58.1  772.28    67.8  771.13
    87.1  769.77   116.2     769   145.2  767.85   183.9  765.17   239.8  764.18
     249  763.08   258.2  761.48   267.4  760.39   276.7  761.47   285.9  762.74
   295.7  763.47   325.2  763.97   364.6  765.15     463  766.87   492.5   768.2
   502.3  769.19   512.1  770.61   531.8   772.6   541.6  775.11   551.5  780.05
   571.2  792.14     581  797.73   590.8  802.62   600.7  806.64   630.2  817.13
#Mann= 3 , 0 , 0
       0     .07       0   258.2    .045       0   276.7     .05       0
Bank Sta=258.2,276.7
XS Rating Curve= 0 ,0
Exp/Cntr=0.3,0.1

Type RM Length L Ch R = 1 ,3577.8  ,801.6,801.5,799.8
XS GIS Cut Line= 4
     1565791.357      234678.873     1565872.954      234881.998
     1565893.788      235006.998     1565916.357      235487.901
#Sta/Elev= 30
       0  901.49    28.6  891.43    38.1  887.79    47.6  883.59    76.1  869.36
   104.7  854.51   209.4  798.92   218.9  794.29   238.4  787.18   248.2  783.31
   267.6  774.76   287.1  765.12   290.7   763.8   296.9  761.52   306.6  760.52
   355.4  762.83   502.8  767.77     552  769.19   561.8  769.81   581.4  772.77
   591.2  773.49   601.1  774.91   610.9  778.81   620.7  784.53     660  809.74
   669.9  814.97   679.7  819.02   699.3  826.01   758.3  846.51   827.1  870.88
#Mann= 3 , 0 , 0
       0      .1       0   290.7    .045       0   306.6    .055       0
Bank Sta=290.7,306.6
XS Rating Curve= 0 ,0
Exp/Cntr=0.3,0.1

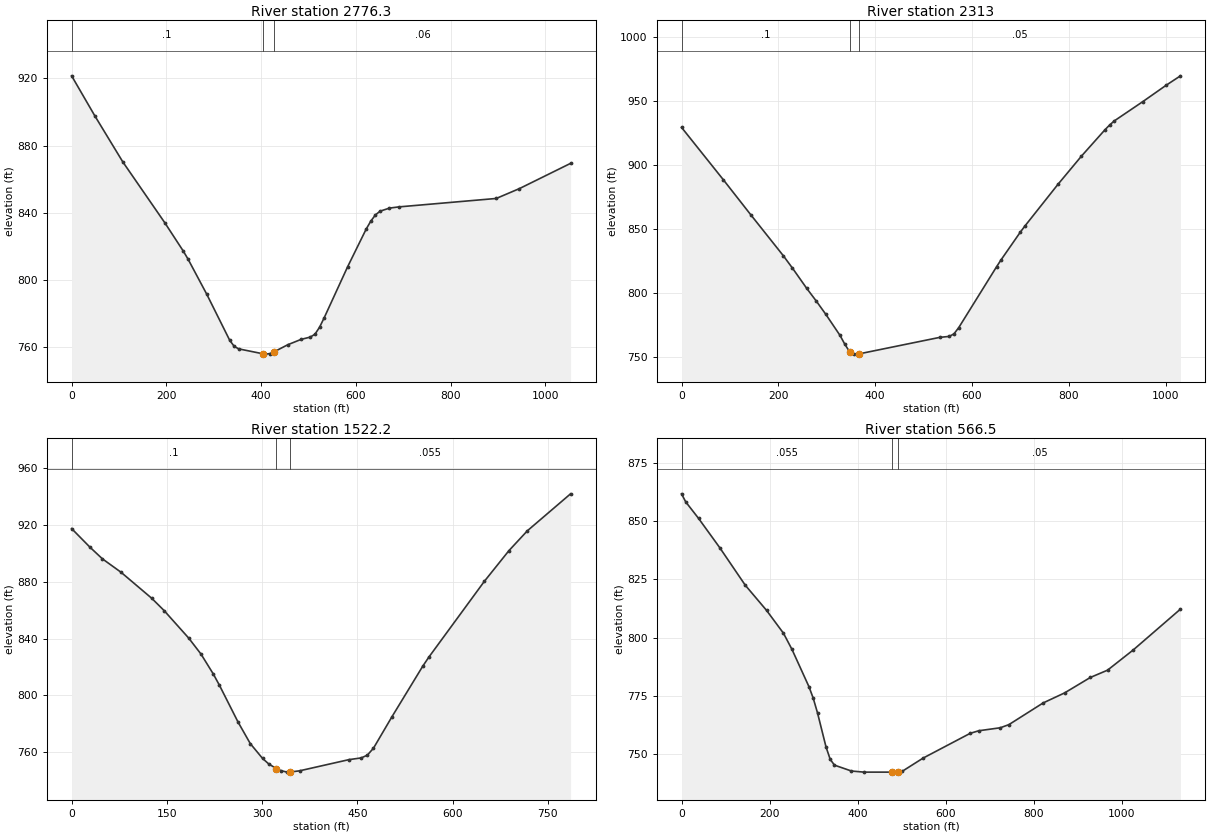
Type RM Length L Ch R = 1 ,2776.3  ,458.8,463.3,466.1
XS GIS Cut Line= 4
     1565140.315      235014.637     1565227.121      235327.137
     1565261.843      235483.387     1565539.621      235979.915
#Sta/Elev= 30
       0   921.5    49.1  897.63   108.1  870.26   196.6  834.11   235.9  817.12
   245.7  812.45     285  791.67   333.8  764.07   343.2   760.5   352.6     759
     403756.1115   409.1  755.86   418.5  756.18   427.9   757.3   456.2  761.43
   484.4  764.63     504  766.02   513.8  767.74   523.6  771.96   533.4  777.62
   582.5  807.76   621.7  830.21   631.5  834.98   641.3   838.7   651.2  840.94
   670.8  842.76   690.4  843.48   896.4  848.51   945.4  854.39  1053.3   869.4
#Mann= 3 , 0 , 0
       0      .1       0     403    .045       0   427.9     .06       0
Bank Sta=403,427.9
XS Rating Curve= 0 ,0
Exp/Cntr=0.3,0.1

Type RM Length L Ch R = 1 ,2313    ,779.6,790.8,799.1
XS GIS Cut Line= 4
     1564813.926      235045.887     1564810.454      235275.054
     1564815.309      235628.391      1564866.01      236073.665
#Sta/Elev= 30
       0  929.57      86  888.72   143.2  861.03   210.1  829.11   229.2  819.29
   258.6  803.46   278.3  793.54   297.9   783.2   327.4   766.6   337.2  759.77
     347  753.91   347.8  753.75   356.8  751.92   366.6  752.11   533.5  765.05
   553.1  765.81   562.9  767.83   572.8  772.77   650.8  820.36   660.5  826.01
   699.5  847.29   709.2  852.21   777.4  884.83   826.1  907.02   874.8  927.72
   884.6   931.5   894.3  934.72   952.8  949.71  1001.5  962.66  1030.7  969.95
#Mann= 3 , 0 , 0
       0      .1       0   347.8    .045       0   366.6     .05       0
Bank Sta=347.8,366.6
XS Rating Curve= 0 ,0
Exp/Cntr=0.3,0.1

Type RM Length L Ch R = 1 ,1522.2  ,961.2,955.7,941.7
XS GIS Cut Line= 3
     1564275.732      234900.054     1564133.431      235197.697
      1563928.51      235604.915
#Sta/Elev= 30
       0  917.41    29.1  904.21    48.5   896.1    77.6  886.74   126.1  868.38
   145.6  859.72   184.4  840.32   203.8  829.04   223.2     815   232.9  807.03
     262   781.3   281.4  766.03   300.8  755.57   310.5   751.7   322.4  748.48
   329.9  746.96   339.6  745.96  343.46745.9839     359  746.88   436.6  754.74
     456  755.96   465.7  757.89   475.4  762.81   504.5  784.94     553  820.53
   562.7  826.97     650  880.26   688.8  901.91   717.9  915.91   785.8  941.87
#Mann= 3 , 0 , 0
       0      .1       0   322.4    .045       0  343.46    .055       0
Bank Sta=322.4,343.46
XS Rating Curve= 0 ,0
Exp/Cntr=0.3,0.1

Type RM Length L Ch R = 1 ,566.5   ,551,566.5,580.1
XS GIS Cut Line= 4
     1563727.121      234455.609     1563439.789      234727.887
     1563405.066      234866.775     1563300.038      235452.137
#Sta/Elev= 30
       0  861.75     9.6  858.28    38.6  851.24    86.9  838.63   144.8  822.54
   193.1  811.75   231.7   801.9     251  794.97   289.6  778.96   299.3  774.01
     309  767.72   328.3  753.14   337.9  747.76   347.6  745.29   386.2  742.77
   414.9   742.3   477.5   742.3   492.5  742.33   500.8  742.57   548.8  748.31
     656  758.96   675.5  760.06   724.2  761.34   743.8  762.68   821.7     772
   870.5  776.31     929  782.94     968  786.06  1026.5  794.76  1133.7  812.27
#Mann= 3 , 0 , 0
       0    .055       0   477.5    .045       0   492.5     .05       0
Bank Sta=477.5,492.5
XS Rating Curve= 0 ,0
Exp/Cntr=0.3,0.1

Chan Stop Cuts=-1
Use User Specified Reach Order=0
Composite Channel Slope=5